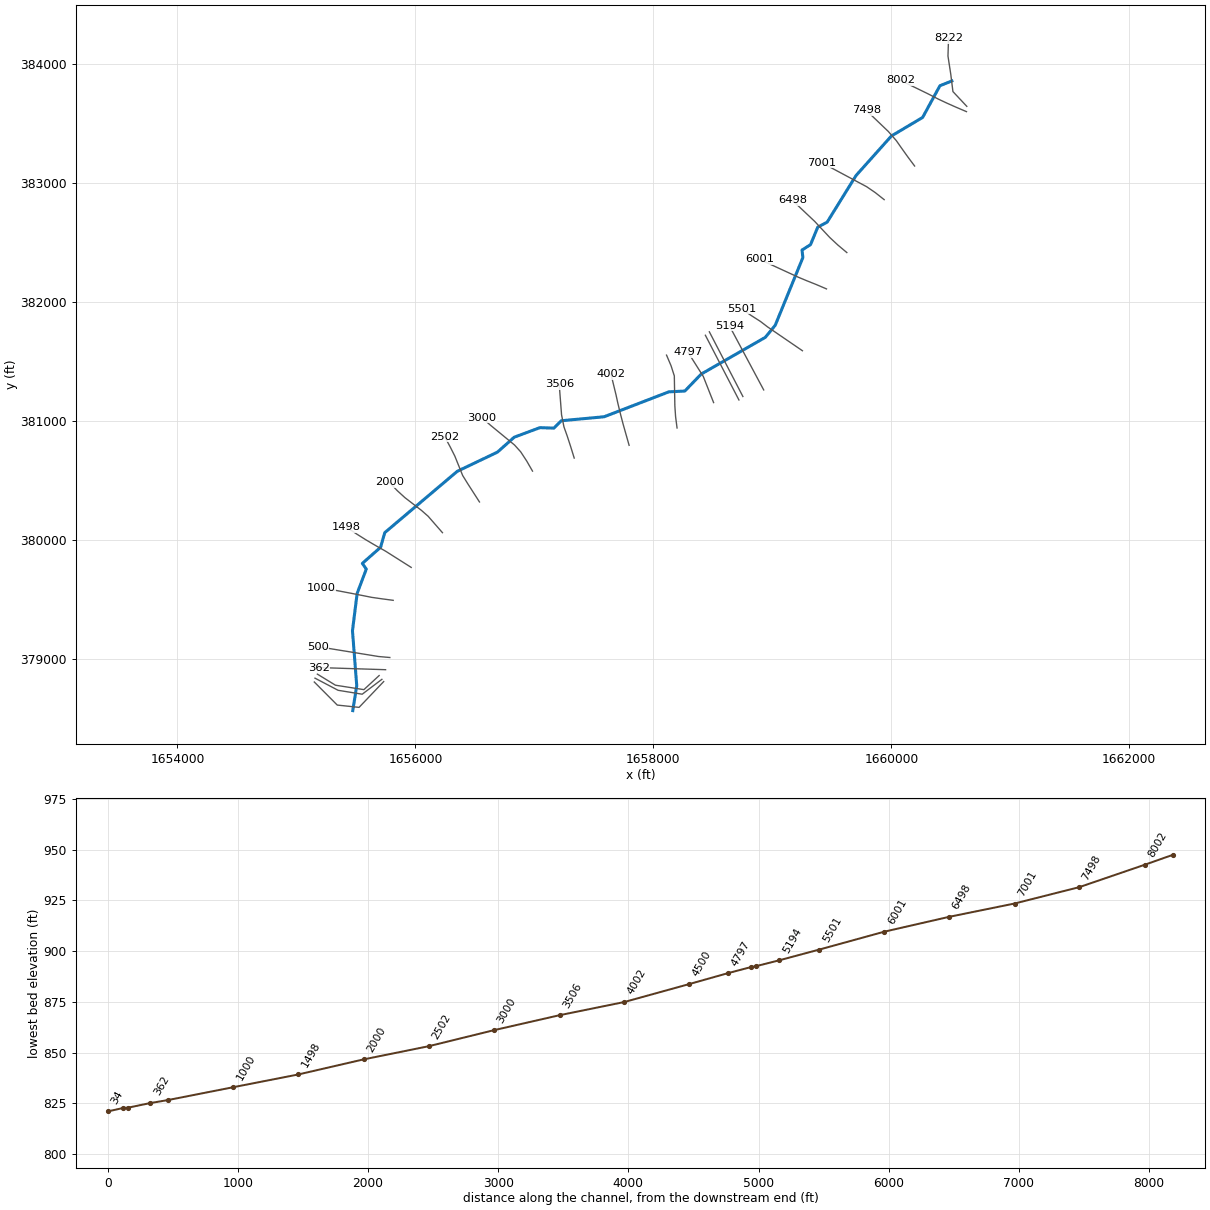
--- NFRCHWDRN.prj (project) ---

Proj Title=NFRCHWDRN
Current Plan=p01
Default Exp/Contr=0,0
English Units
Geom File=g01
Flow File=f01
Plan File=p01
BEGIN DESCRIPTION:
---------- MODELED AS PART OF WVEMD CTP PROGRAM, 2023----------
Stream Name: North Fork Richwood Run
Flood Zone:  AFH
Wetzel County, WV
HEC-RAS Version: RAS 6.3
Vertical Datum: NAVD88
Projection: NAD 1983 StatePlane West Virginia S FIPS 4702 (US Feet)
Terrain: 1-meter West Virginia FEMA R3 South Central (collected 2018-2020)
Land Use: 2019 NLCD
Hydrologic Method:
WV 2010 Regional Regression Equations
Additional Model Notes:
None
END DESCRIPTION:
DSS Export Rating Curves= 0
DSS Export Rating Curve Sorted= 0
DSS Export Volume Flow Curves= 0
DXF OffsetX= 0
DXF OffsetY= 0
DXF ScaleX= 0
DXF ScaleY= 0

--- NFRCHWDRN.p01 (plan) ---

Plan Title=Floodplain
Program Version=6.30
Short Identifier=Floodplain
Geom File=g01
Flow File=f01
Subcritical Flow
K Sum by GR= 0
Std Step Tol= 0.01
Critical Tol= 0.01
Num of Std Step Trials= 20
Max Error Tol= 0.3
Flow Tol Ratio= 0.001
Split Flow NTrial= 30
Split Flow Tol= 0.02
Split Flow Ratio= 0.02
Log Output Level= 0
Friction Slope Method= 1
Unsteady Friction Slope Method= 2
Unsteady Bridges Friction Slope Method= 1
Parabolic Critical Depth
Global Vel Dist= 0 , 0 , 0
Global Log Level= 0
CheckData=False
Encroach Param=-1 ,0,0, 0
Mapping Interval=1HOUR
Computation Time Step Use Courant=        0
Computation Time Step Use Time Series=    0
Computation Time Step Count To Double=0
Computation Time Step Max Doubling=0
Computation Time Step Max Halving=0
Computation Time Step Residence Courant=0
Run HTab= 0
Run UNet= 0
Run Sediment= 0
Run PostProcess= 0
Run WQNet= 0
Run RASMapper=-1
UNET Theta= 0
UNET Theta Warmup= 0
UNET ZTol= 0
UNET ZSATol= 0
UNET MxIter= 0
UNET Max Iter WO Improvement= 0
UNET MaxInSteps= 0
UNET DtIC= 0
UNET DtMin= 0
UNET MaxCRTS= 0
UNET WFStab= 0
UNET SFStab= 0
UNET WFX= 1
UNET SFX= 1
UNET Gravity=32.17405
UNET 1D Methodology=Finite Difference
UNET DSS MLevel= 1
UNET Pardiso=0
UNET DZMax Abort= 0
UNET Use Existing IB Tables= 0
UNET Froude Reduction=False
UNET Froude Limit= 0
UNET Froude Power= 0
UNET D1 Cores= 0
UNET WindReference=Eulerian
UNET WindDragFormulation=Hsu (1988)
UNET D2 Coriolis=0
UNET D2 Cores= 0
UNET D2 Theta= 1
UNET D2 Theta Warmup= 1
UNET D2 Z Tol= 0.01
UNET D2 Volume Tol= 0.01
UNET D2 Max Iterations= 20
UNET D2 Equation= 0
UNET D2 RampUpFraction=0.1
UNET D2 TimeSlices= 1
UNET D2 Turbulence Formulation=Non-Conservative (original)
UNET D2 Eddy Viscosity=0.3
UNET D2 Transverse Eddy Viscosity=0.1
UNET D2 Smagorinsky Mixing=0
UNET D2 BCVolumeCheck=0
UNET D2 Cores=0
UNET D2 SolverType=PARDISO (Direct)
UNET D2 Minimum Iterations= 3
UNET D2 Maximum Iterations= 30
UNET D2 Restart Number= 10
UNET D2 Relaxation Coeff=1.3
UNET D2 SOR Precondition Iterations= 10
UNET D2 ILUT Maximum Fill= 8
UNET D2 ILUT Tolerance=1E-08
UNET D2 Convergence Tolerance=0.00001
UNET D1D2 MaxIter= 0
UNET D1D2 ZTol=0.01
UNET D1D2 QTol=0.1
UNET D1D2 MinQTol=1
Write IC File= 0
Write IC File at Fixed DateTime=0
Write IC File at Sim End=0
Echo Input=False
Echo Parameters=False
Echo Output=False
Write Detailed= 0
HDF Write Warmup=0
HDF Write Time Slices=0
HDF Flush=0
HDF Compression= 1
HDF Chunk Size= 1
HDF Spatial Parts= 1
HDF Use Max Rows=0
HDF Fixed Rows= 1
Calibration Method= 0
Calibration Iterations= 20
Calibration Max Change=0.05
Calibration Tolerance=0.2
Calibration Maximum=1.5
Calibration Minimum=0.5
Calibration Optimization Method= 1
WQ AD Non Conservative
WQ ULTIMATE=-1
WQ Max Comp Step=1HOUR
WQ Output Interval=15MIN
WQ Output Selected Increments= 0
WQ Output face flow=0
WQ Output face velocity=0
WQ Output face area=0
WQ Output face dispersion=0
WQ Output cell volume=0
WQ Output cell surface area=0
WQ Output cell continuity=0
WQ Output cumulative cell continuity=0
WQ Output face conc=0
WQ Output face dconc_dx=0
WQ Output face courant=0
WQ Output face peclet=0
WQ Output face adv mass=0
WQ Output face disp mass=0
WQ Output cell mass=0
WQ Output cell source sink temp=0
WQ Output nsm pathways=0
WQ Output nsm derived pathways=0
WQ Create Restart=0
WQ Fixed Restart=0
WQ System Summary=0
WQ Write To DSS=0
Sorting and Armoring Iterations= 10
XS Update Threshold= 0.02
Bed Roughness Predictor= 0
Hydraulics Update Threshold= 0.02
Energy Slope Method= 1
Volume Change Method= 1
Sediment Retention Method= 0
Sediment TS Multiplier= 1
Warm Up Method= 0
XS Weighting Method= 0
Number of US Weighted Cross Sections= 1
Number of DS Weighted Cross Sections= 1
Upstream XS Weight=0
Main XS Weight=1
Downstream XS Weight=0
Number of DS XS's Weighted with US Boundary= 1
Upstream Boundary Weight= 1
Weight of XSs Associated with US Boundary= 0
Number of US XS's Weighted with DS Boundary= 1
Downstream Boundary Weight= 0.5
Weight of XSs Associated with DS Boundary= 0.5
Percentile Method= 0
Sediment Output Level= 3
Mass or Volume Output= 0
Output Increment Type= 1
Profile and TS Output Increment= 1
Transport Output Increment 1
XS Output Flag= 0
XS Output Increment= 10
Read HDF5 Sediment Hotstart= 0
Sediment Hotstart Type= 0
Write Gradation File= 0
Read Gradation Hotstart= 0
Write HDF5 File= 1
Write Binary Output= 1
Write DSS Sediment File= 0
DSS Sediment Output Type= 1
SV Curve= 0
Specific Gage Flag= 0
Subcell Erosion Methods= 0
Subcell Deposition Methods= 0
Advection Scheme= 1
Matrix Solver= 0
Implicit Weighting Factor= 1
Maximum Outer Loop Convergence Iterations= 5
Convergence Maximum Absolute= 0.001
Convergence RMSE= 0.0001
Grain Fractions Max Abs Error= 0.001
Max Subgrid Regions= 1
Max Subgrid Length Scale= 3.402823E+38
Initial Layer Thickness= 3.402823E+38
Min Layer Thickness= 3.402823E+38
Max Layer Thickness= 3.402823E+38
Number of Layers= 5

--- NFRCHWDRN.f01 (steady flow) ---

Flow Title=Flow
Program Version=6.30
Number of Profiles= 1
Profile Names=F01pct
River Rch & RM=NFRCHWDRN,Main,8222
     677
River Rch & RM=NFRCHWDRN,Main,6498
     760
River Rch & RM=NFRCHWDRN,Main,4002
     864
River Rch & RM=NFRCHWDRN,Main,1498
    1000
Boundary for River Rch & Prof#=NFRCHWDRN,Main            , 1
Up Type= 0
Dn Type= 3
Dn Slope=0.01264
DSS Import GetInterval= 0
DSS Import GetPeak= 0
DSS Import FillOption= 0

--- NFRCHWDRN.g01 (geometry) ---

Geom Title=Geometry
Program Version=6.30

River Reach=NFRCHWDRN       ,Main
Reach XY= 30
  1660508.712063383859.8475836861660408.39592066383819.724295697
     1660263.156      383553.4291660000.24391151383397.033168992
      1659703.29      383065.008     1659460.575      382673.156
      1659381.62      382631.418     1659321.008      382484.407
      1659249.23      382438.682     1659256.691      382375.827
     1659024.078      381806.341     1658941.002      381705.404
     1658401.423      381395.946     1658264.348      381253.886
      1658130.18       381247.24     1657586.448      381037.888
     1657226.314      381004.243     1657163.591      380942.351
     1657045.208       380946.09     1656830.457      380865.921
     1656689.427      380740.477     1656352.072      380579.642
     1655742.228      380063.9061655707.11260727379940.671925995
      1655553.48      379805.241     1655586.976      379757.655
     1655509.881       379552.69     1655470.802      379239.261
     1655506.691      378777.225     1655473.264      378568.099

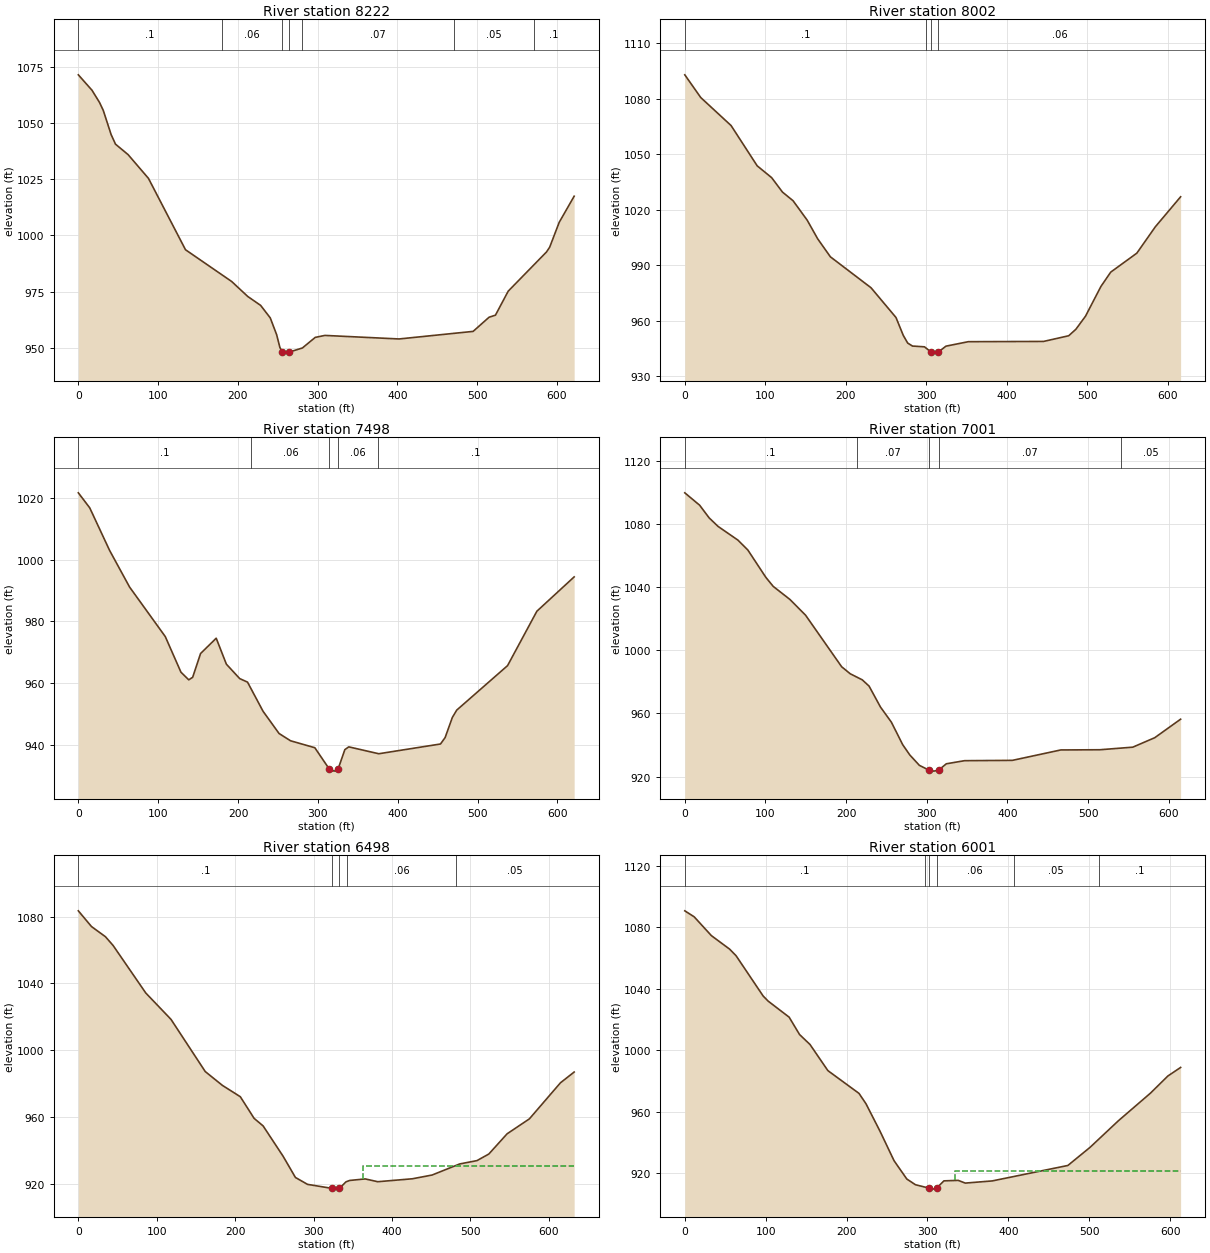
Type RM Length L Ch R = 1 ,8222    ,219.7,219.7,219.7
XS GIS Cut Line= 5
1660634.30532333383646.5452667451660517.81183637383770.575111867
1660499.94532826383914.2922474231660476.17475797 384069.02551859
 1660480.9666087 384219.16974644
#Sta/Elev= 30
       0 1071.68    17.1 1064.82    26.6 1059.34    31.3 1055.79    41.1 1045.05
    46.6 1040.75    62.4 1036.08    87.9 1025.51   134.4  993.64   192.3  979.47
   212.4  972.81   228.6  968.82   240.7  963.23   248.7  955.73   252.8  950.01
   255.9  948.05   259.5  947.51   264.8     948     281  949.81   297.1  954.53
   309.2  955.41   402.2  953.83   495.1  957.21   515.1  963.53   523.1  964.45
   539.1  975.16   587.1  992.64   591.1  994.78   603.1 1005.91   621.8 1017.52
#Mann= 7, -1 ,  0
       0     0.1       0  180.16    0.06       0   255.9   0.045       0
   264.8    0.06       0  280.16    0.07       0  471.53    0.05       0
  571.53     0.1       0
Bank Sta=255.9,264.8
XS Rating Curve= 0 ,0
Exp/Cntr(USF)=0,0
Exp/Cntr=0.3,0.1

Type RM Length L Ch R = 1 ,8002    ,504.4,504.4,504.4
XS GIS Cut Line= 6
1660631.55721368383601.9840784221660544.14826776383639.291746587
   1660462.98406383675.4567005041660394.57441993383707.691216096
1660305.50176342383753.1822668461660075.19316892383865.530139253
#Sta/Elev= 30
       0 1092.92    19.8 1080.65    57.5  1065.5    89.9 1043.75   107.9 1037.34
   121.3 1029.56   134.5 1024.87     152 1014.39   165.1 1004.27   180.8  994.59
   231.3  977.86   262.3  961.79   271.3  952.16   276.8  947.98   282.8  946.36
   297.7  945.94   306.1943.0333   311.7  942.54   314.5942.9933   324.4  946.31
   352.1  948.72   445.6  948.86   476.8  951.93   485.7  955.42   497.7  962.52
   516.8  978.56     529  986.31   561.4  996.55   584.4 1010.81   615.8 1027.02
#Mann= 4, -1 ,  0
       0     0.1       0  299.52    0.06       0   306.1   0.045       0
   314.5    0.06       0
Bank Sta=306.1,314.5
XS Rating Curve= 0 ,0
Exp/Cntr(USF)=0,0
Exp/Cntr=0.3,0.1

Type RM Length L Ch R = 1 ,7498    ,496.6,496.6,496.6
XS GIS Cut Line= 6
1660195.66372851383145.0712783341660138.01981492383222.490086749
1660085.62589084383295.9850185071660041.21915551383359.250640005
1659975.00439292383435.1002258361659789.82759793   383612.226512
#Sta/Elev= 30
       0 1021.62    14.3 1016.75    39.2 1002.95    64.2   991.1   108.9  975.06
   128.5  963.54   138.3  961.05   143.2  961.87   153.1  969.57   172.7  974.53
   185.4  966.13   202.1  961.45   211.9  960.31   231.4  950.85   251.4  943.67
   265.8  941.31   296.2  939.06   314.4  932.12   320.5  931.48   325.3  932.12
   333.8  938.44   338.7  939.34   376.3  937.11   453.6  940.27   459.4  942.35
   468.4  948.84   473.9  951.24   537.6  965.65   574.3  983.27     621  994.39
#Mann= 5, -1 ,  0
       0     0.1       0  216.78    0.06       0   314.4   0.045       0
   325.3    0.06       0  374.76     0.1       0
Bank Sta=314.4,325.3
XS Rating Curve= 0 ,0
Exp/Cntr(USF)=0,0
Exp/Cntr=0.3,0.1

Type RM Length L Ch R = 1 ,7001    ,503.1,503.1,503.1
XS GIS Cut Line= 6
1659939.82172051382862.4383134251659864.91898318382921.692788094
1659792.20849867382971.4000377511659637.84496225383053.843442425
1659571.68892659383089.1757208411659411.81194976 383174.56268917
#Sta/Elev= 30
       0 1099.82    18.4 1091.97    30.2 1083.95    41.2 1078.56    65.9 1069.84
    78.2 1063.56   100.5 1046.25   109.6 1040.54   130.4 1032.22   149.8 1022.23
   194.5  989.58   205.2  985.11     220  981.31   228.5  977.32   242.6  964.07
   256.2  954.42   270.2  940.18   279.1  933.61   290.9  927.08     303 923.996
   308.6  923.43   314.6  924.02   324.3  928.08   346.9  930.05   406.2  930.25
   466.2  936.85   514.7  936.98   555.5  938.62   582.7  944.61   614.8  956.35
#Mann= 5, -1 ,  0
       0     0.1       0  213.58    0.07       0     303   0.045       0
   314.6    0.07       0  541.08    0.05       0
Bank Sta=303,314.6
XS Rating Curve= 0 ,0
Exp/Cntr(USF)=0,0
Exp/Cntr=0.3,0.1

Type RM Length L Ch R = 1 ,6498    ,496.9,496.9,496.9
XS GIS Cut Line= 6
1659626.00705943382417.7498983441659550.23555742382481.360991582
1659481.91417176382544.9635546651659426.80174917 382603.96573326
1659356.29139151 382679.296947421659169.99025492382855.239508927
#Sta/Elev= 30
       0 1083.49    16.8 1074.07    34.6 1067.98    44.3 1062.78      86 1034.31
   118.2  1018.5   161.9  987.24   183.8  978.96   206.6  972.19   224.2  959.23
   235.7   954.7   261.2  936.53   276.9  923.84   292.3  919.71   323.8  917.29
   329.6  916.86     333  917.26   341.3   921.2   346.1  922.05   365.9  922.97
   381.9   921.3     426  923.05   451.2   925.3   486.5  931.94   508.5  933.94
   523.6  937.89   546.9  949.99   575.3  958.93   614.9  980.51   632.4  986.97
#Mann= 5, -1 ,  0
       0     0.1       0   323.8   0.045       0     333     0.1       0
  343.01    0.06       0   481.2    0.05       0
#XS Ineff= 2 , 0
                          362.83          930.47
Permanent Ineff=
       F       F
Bank Sta=323.8,333
XS Rating Curve= 0 ,0
Exp/Cntr(USF)=0,0
Exp/Cntr=0.3,0.1

Type RM Length L Ch R = 1 ,6001    ,500,500,500
XS GIS Cut Line= 6
1659455.03397617382112.2774121761659368.48165584382149.210409179
1659287.14356393382181.7661183331659217.92093334382210.748015761
1659058.93503085382283.8813996761658894.27164626382359.628295422
#Sta/Elev= 30
       0 1090.73    11.6 1086.83    32.9 1074.57    55.4  1065.8    63.4  1061.5
    96.9 1035.26   103.1 1031.94     129 1021.51   141.9 1010.19   154.8 1003.72
   176.9  986.71   215.4  971.88     224  965.14   241.4  947.22   258.7  928.08
   274.5  916.14   285.2  912.43   302.1910.1916   307.2  909.57   311.2910.1912
   320.4  914.95     338  915.27   346.8   913.5   380.1  914.91   473.6  924.97
   500.9  936.71   536.1  954.09   575.8  972.09   597.2  983.19     613  988.78
#Mann= 6, -1 ,  0
       0     0.1       0  296.76    0.06       0   302.1   0.045       0
   311.2    0.06       0  406.76    0.05       0  511.76     0.1       0
#XS Ineff= 2 , 0
                          334.65           921.6
Permanent Ineff=
       F       F
Bank Sta=302.1,311.2
XS Rating Curve= 0 ,0
Exp/Cntr(USF)=0,0
Exp/Cntr=0.3,0.1

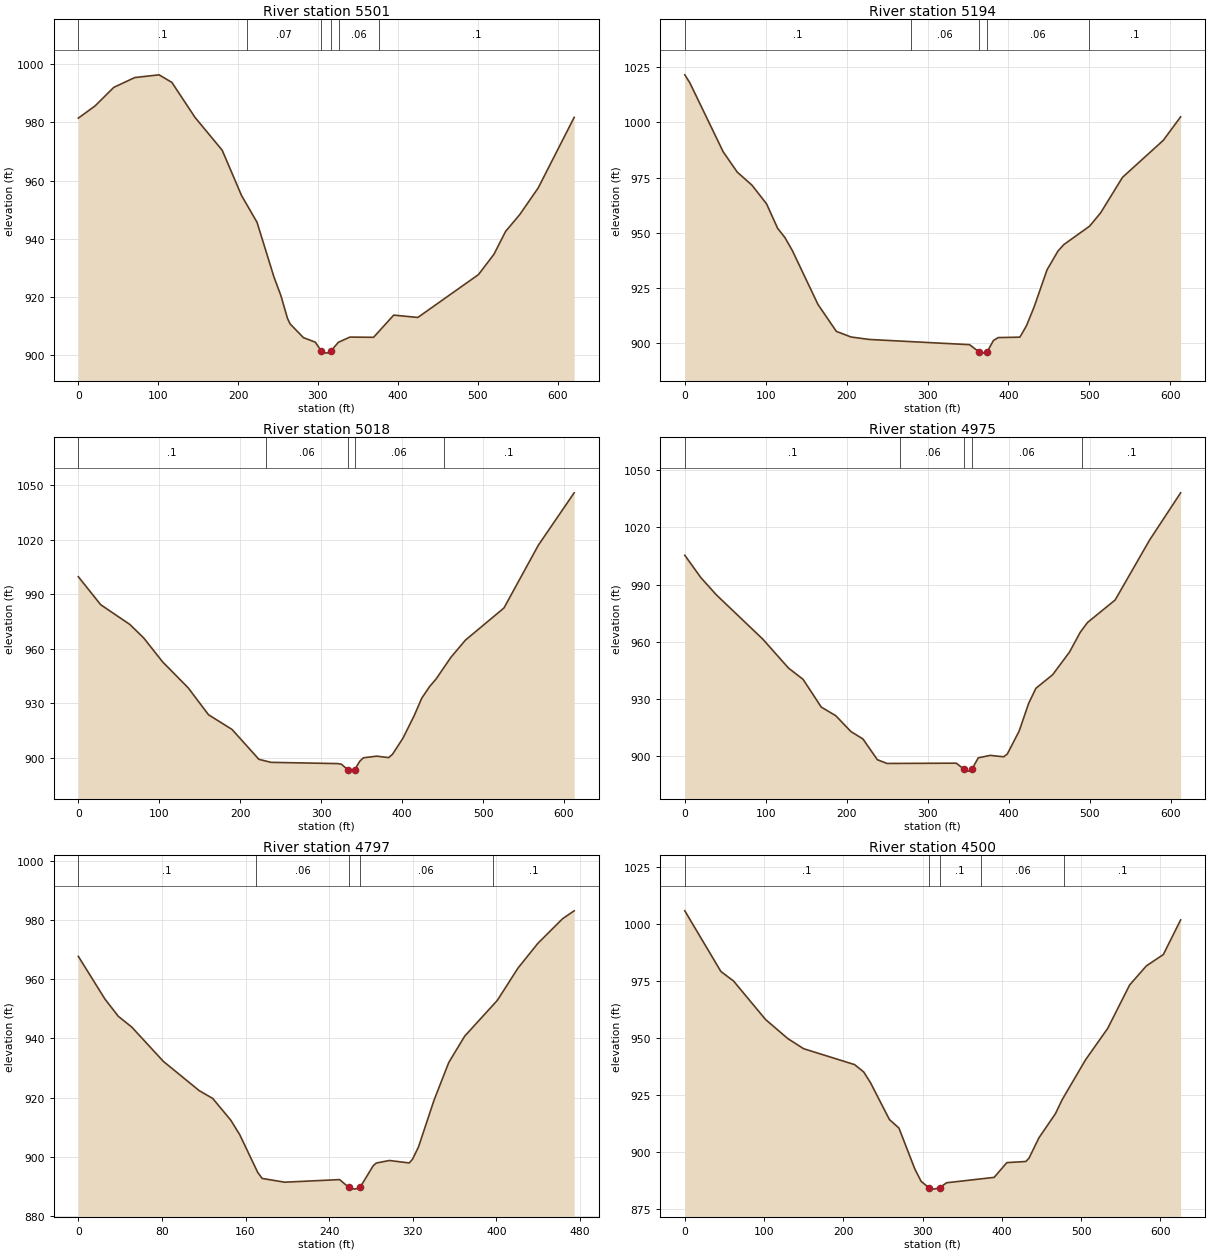
Type RM Length L Ch R = 1 ,5501    ,306.8,306.8,306.8
XS GIS Cut Line= 6
1659252.72630993 381592.685275511659041.24051243381737.384461179
1658958.70983759381793.8531802591658898.96684684381839.537800178
 1658822.9263165381888.1328473391658742.09642567 381945.27380918
#Sta/Elev= 30
       0  981.42      21  985.63    44.4  991.99    70.6  995.35   101.1  996.29
   117.1  993.69   146.1  981.67   180.1  970.41   204.3  954.87   223.7  945.67
   244.9  926.89   253.6  920.49   261.8   912.7   265.1  910.79   281.8  906.07
   296.7   904.5   304.4901.3664   310.9  900.75   315.8  901.35   325.5  904.46
     340  906.26   369.6  906.18   394.8   913.8     425  912.99   500.9  927.71
   520.3  934.68   534.9  942.55   552.7  948.35   575.7  957.47   620.7  981.67
#Mann= 6, -1 ,  0
       0     0.1       0  211.25    0.07       0   304.4   0.045       0
   315.8    0.07       0  326.25    0.06       0  376.25     0.1       0
Bank Sta=304.4,315.8
XS Rating Curve= 0 ,0
Exp/Cntr(USF)=0,0
Exp/Cntr=0.3,0.1

Type RM Length L Ch R = 1 ,5194    ,176.4,176.4,176.4
XS GIS Cut Line= 2
1658927.16899269381263.3784523031658638.27844912381803.692506483
#Sta/Elev= 30
       0 1021.55     6.1 1018.03    47.4  986.71    64.8  977.48      83  971.58
   101.1  963.07   114.7  952.04   123.8  947.79   132.9  941.95   164.6  917.51
   187.3  905.33   205.4  902.79   228.1  901.67   351.9  899.31   363.7     896
   368.7  895.48   373.5895.9872   381.4   901.2   387.3  902.52   414.1  902.72
   422.2  907.88   431.7  916.43   447.6  933.19   461.2  941.76   468.5  944.68
   500.3  953.02   513.9  959.05   540.9  975.12   591.3  991.88   612.7 1002.52
#Mann= 5, -1 ,  0
       0     0.1       0     280    0.06       0   363.7   0.045       0
   373.5    0.06       0     500     0.1       0
Bank Sta=363.7,373.5
XS Rating Curve= 0 ,0
Exp/Cntr(USF)=0,0
Exp/Cntr=0.3,0.1

Type RM Length L Ch R = 1 ,5018    ,43,43,43
XS GIS Cut Line= 6
1658752.35737525381207.9957980291658668.92479933381368.901316114
1658634.40059017381435.4828758611658588.36918617381524.258288868
1658513.56717042381668.5181709451658470.41272916381751.745038606
#Sta/Elev= 30
       0  999.73    27.6  984.31    63.7   973.4    80.7  966.02   104.2  952.76
   135.8  938.46   160.8  923.68   189.9  915.57   223.1   899.1     238  897.45
   320.5  896.76     325  896.41   332.9  893.36   338.5  892.61   341.2 893.365
   347.7  898.05   352.1  899.95   368.5  900.86   383.4  900.07   388.1  901.88
   401.2  910.91   415.1  923.37   424.2  932.77   433.8  939.13   442.2  943.53
   460.2  955.29   478.2  964.79   525.8   982.5   568.3 1017.11   612.5 1045.94
#Mann= 5, -1 ,  0
       0     0.1       0  231.25    0.06       0   332.9   0.045       0
   341.2    0.06       0  451.25     0.1       0
Bank Sta=332.9,341.2
XS Rating Curve= 0 ,0
Exp/Cntr(USF)=0,0
Exp/Cntr=0.3,0.1

Type RM Length L Ch R = 1 ,4975    ,177.6,177.6,177.6
XS GIS Cut Line= 6
1658719.10632453381178.838996785 1658635.6737486 381339.74451487
1658601.14953945381406.3260746171658555.11813544381495.101487624
1658480.31611969381639.3613697011658437.16167844381722.588237362
#Sta/Elev= 30
       0 1005.35    19.9  993.61    39.1  984.55    96.5   961.3   128.1  946.18
   146.1  940.26   168.6   925.7   186.6  921.15   205.2  912.87   220.1  908.96
   237.9  898.08   249.8  896.13   335.3  896.27   345.4  892.98   350.6   892.1
   354.6892.9959   362.5  899.07   377.3  900.36   393.9  899.62   398.4  901.08
     413  913.08   424.8  927.68   433.7  935.56   454.5  942.72   475.3  954.62
   488.5  964.95   497.5   970.1   531.6  981.89   574.1 1013.31   612.5 1038.13
#Mann= 5, -1 ,  0
       0     0.1       0  266.25    0.06       0   345.4   0.045       0
   354.6    0.06       0  491.25     0.1       0
Bank Sta=345.4,354.6
XS Rating Curve= 0 ,0
Exp/Cntr(USF)=0,0
Exp/Cntr=0.3,0.1

Type RM Length L Ch R = 1 ,4797    ,297,297,297
XS GIS Cut Line= 3
1658506.15785923381156.893200749 1658419.3920987381376.765525717
1658292.20138157381577.904334207
#Sta/Elev= 30
       0  967.71    25.4  953.32    38.3  947.44    51.2   943.8    81.3  932.26
   115.7  922.35   128.6  919.72   145.8  912.41   154.4  907.51   171.6  894.78
   175.9  892.71   197.4  891.44     250  892.32   258.9  889.66   264.5   889.1
   269.5889.6523   282.1  896.98     285   897.9   297.6  898.77   316.6  897.94
   319.8  899.22   325.6  903.47   340.2     919   354.4  931.85   369.7  940.77
   400.9  952.85   420.7  963.76   439.6  972.07   463.3  980.41   474.4  983.08
#Mann= 5, -1 ,  0
       0     0.1       0     170    0.06       0   258.9   0.045       0
   269.5    0.06       0  396.37     0.1       0
Bank Sta=258.9,269.5
XS Rating Curve= 0 ,0
Exp/Cntr(USF)=0,0
Exp/Cntr=0.3,0.1

Type RM Length L Ch R = 1 ,4500    ,498.4,498.4,498.4
XS GIS Cut Line= 6
1658199.03484775380943.4434637581658186.62575184381039.508560345
1658180.50929426381129.5497188421658176.05654725381380.962929919
1658148.64846559381466.4086251711658110.62491959381555.638105512
#Sta/Elev= 30
       0 1005.94    45.5  979.32    61.6  975.08   101.9   958.2     130  949.82
     150  945.38   214.1  938.42   225.6  935.21   234.1  930.55   258.1  914.29
   270.1  910.55   290.1  892.61   298.1  887.14     308884.3186   314.1  883.73
   321.3   884.3   330.1  886.52   390.2  888.89   406.2  895.37   430.2  895.87
   434.2  897.35   446.6  906.21   467.6  916.92     476  923.02   505.4  940.48
   533.5  954.36   561.1  973.38   582.2  981.76   603.6  986.75   625.4 1001.94
#Mann= 5, -1 ,  0
       0     0.1       0     308   0.045       0   321.3     0.1       0
  373.56    0.06       0  478.65     0.1       0
Bank Sta=308,321.3
XS Rating Curve= 0 ,0
Exp/Cntr(USF)=0,0
Exp/Cntr=0.3,0.1

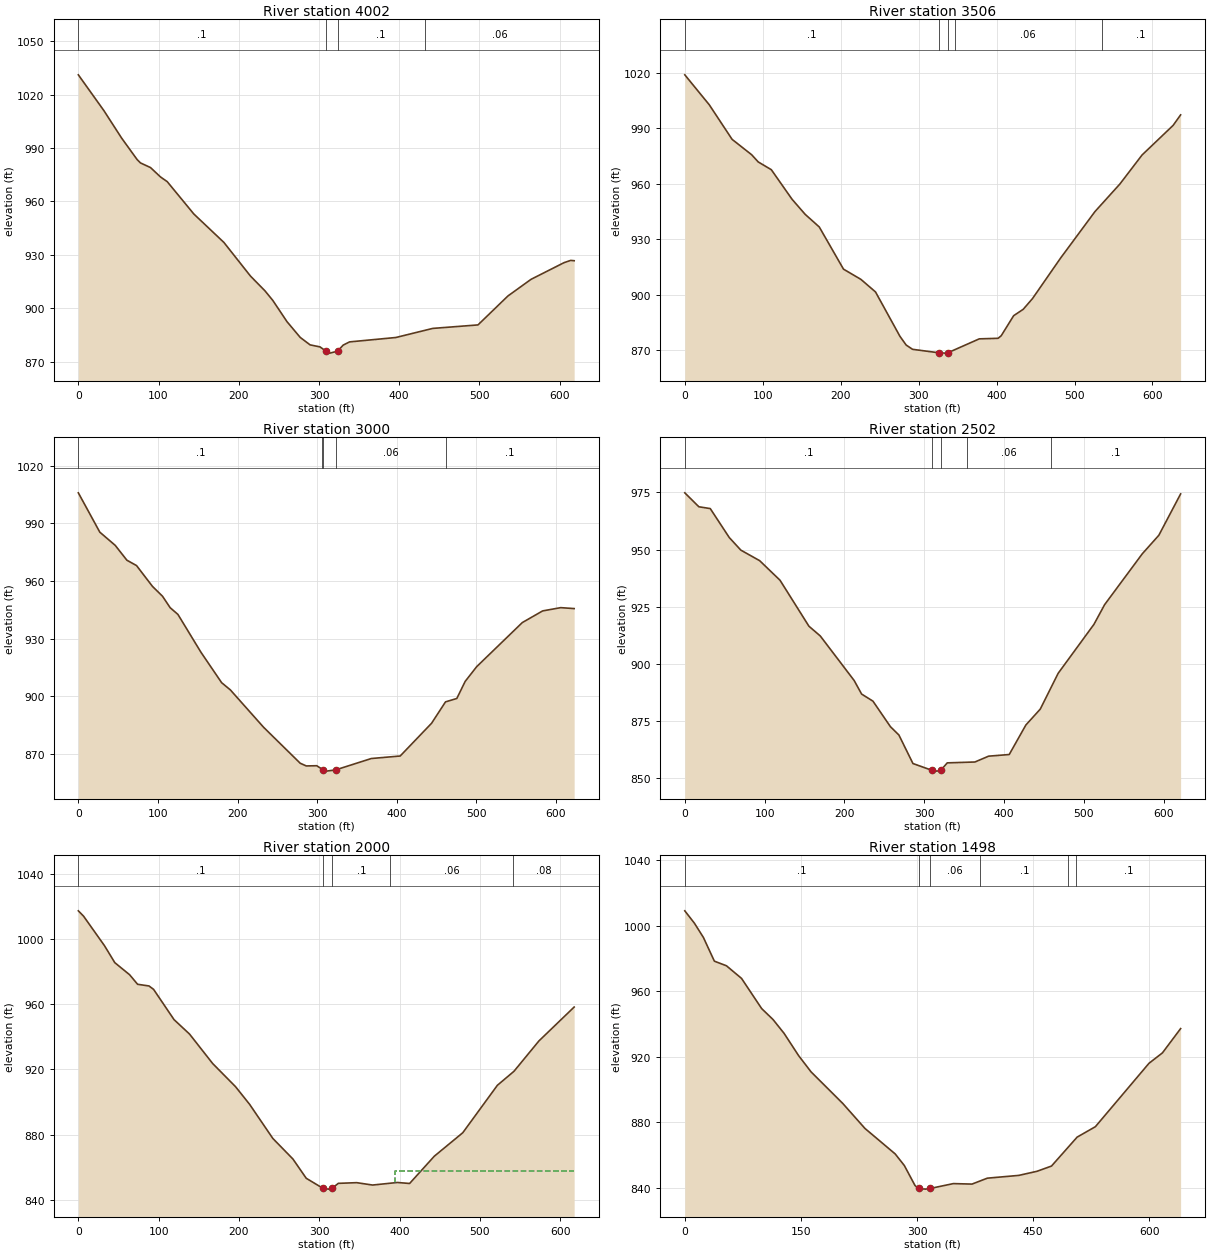
Type RM Length L Ch R = 1 ,4002    ,496,496,496
XS GIS Cut Line= 6
1657795.94149384380797.8929018381657745.43962634 380976.50409317
1657726.01151559381050.2067016661657702.28616934381147.381376088
1657686.25995468381220.6489460921657643.43130018381396.750956088
#Sta/Elev= 30
       0 1031.09    31.8 1011.05    53.9  995.63    73.3  983.53    77.5  981.64
      90  979.03   102.4  973.79   110.8  971.15     144  952.98   181.5  937.01
   214.6  918.14   232.6  909.89   242.4  904.51   260.1  892.58   276.6  883.72
   288.9  879.54   301.3  878.39   308.6 876.048   313.6   874.9   323.2876.0073
   330.1  879.38   338.1   881.2   395.8  883.67   441.9  888.78   498.2  890.73
   535.5  906.96   564.3   916.3   605.5  925.68   613.8  926.94   618.1  926.76
#Mann= 4, -1 ,  0
       0     0.1       0   308.6   0.045       0   323.2     0.1       0
  431.86    0.06       0
Bank Sta=308.6,323.2
XS Rating Curve= 0 ,0
Exp/Cntr(USF)=0,0
Exp/Cntr=0.3,0.1

Type RM Length L Ch R = 1 ,3506    ,506.1,506.1,506.1
XS GIS Cut Line= 6
1657334.60186534380690.5735626671657305.33420734380785.113399833
1657276.01668067380875.0827080911657248.17323242380953.164572924
 1657228.1699916 381054.533464671657208.51779993381310.028688595
#Sta/Elev= 30
       0 1019.01    31.4  1002.8    60.7  984.09    85.8  975.76    94.2  971.88
     111  967.68   137.6  951.68   154.5  943.49   172.5   936.7   203.6  913.87
     226  908.32   244.7  901.52     276  877.53     284   872.8   292.2  870.49
   326.1868.5969   332.9  868.43   337.3   868.6   377.8  876.15   401.9  876.45
   405.9  877.81   421.9  888.69   434.1  892.12     446   897.9   482.1  919.86
   526.2  945.01   558.3  959.99   586.6  975.62   626.5  991.67   636.1  997.34
#Mann= 5, -1 ,  0
       0     0.1       0   326.1   0.045       0   337.3     0.1       0
  346.49    0.06       0  534.81     0.1       0
Bank Sta=326.1,337.3
XS Rating Curve= 0 ,0
Exp/Cntr(USF)=0,0
Exp/Cntr=0.3,0.1

Type RM Length L Ch R = 1 ,3000    ,498.1,498.1,498.1
XS GIS Cut Line= 6
1656984.01135917380581.1567867551656935.15384534380666.032601252
 1656884.9813735380742.7020673451656833.46999359380799.944078833
 1656630.7302416380966.7117899211656560.36095975381028.669015095
#Sta/Elev= 30
       0 1005.86      27  985.38    46.3  978.54      61  970.79    73.1  968.01
    93.2  957.13   105.7  952.06   115.3  946.09   125.1  942.58   153.9  922.97
     180  907.05   190.9  903.32   232.7  883.85   278.7  865.13   286.3  863.72
   299.4  863.83   307.7  861.68   311.5  861.02   323.3  861.67     368  867.58
   404.3  868.89   443.7  885.93   461.2  897.06   475.4  898.83   485.9  907.71
   500.4   915.4   557.7  938.34   583.2   944.4   605.9   946.1   622.8  945.62
#Mann= 5, -1 ,  0
       0     0.1       0  306.57    0.06       0   307.7   0.045       0
   323.3    0.06       0  461.63     0.1       0
Bank Sta=307.7,323.3
XS Rating Curve= 0 ,0
Exp/Cntr(USF)=0,0
Exp/Cntr=0.3,0.1

Type RM Length L Ch R = 1 ,2502    ,501.3,501.3,501.3
XS GIS Cut Line= 6
1656538.20811692380321.7668855941656437.74079818380478.256402001
1656397.01614209380544.2372411791656331.28103735380706.873726919
1656291.73091958380785.3676644271656246.82385717 380868.30188176
#Sta/Elev= 30
       0  974.83    17.6  968.74    31.9  967.94    55.7  955.29    70.2  949.78
    93.8  945.17   119.3  936.61   155.5  916.52   169.7  912.26   212.1  892.81
   221.5  886.86   235.7  883.76   257.6  872.59   268.2  868.96   285.8  856.49
   309.7853.5122   315.8  853.17   320.6  853.52   328.8  856.78   363.4  857.16
   380.6  859.71   406.4  860.43   427.2  873.31   445.3  880.29   467.7  895.93
   512.5  917.32   525.9  925.95   573.1  948.18   593.8  956.27   621.1  974.35
#Mann= 5, -1 ,  0
       0     0.1       0   309.7   0.045       0   320.6     0.1       0
   353.5    0.06       0  458.93     0.1       0
Bank Sta=309.7,320.6
XS Rating Curve= 0 ,0
Exp/Cntr(USF)=0,0
Exp/Cntr=0.3,0.1

Type RM Length L Ch R = 1 ,2000    ,502.7,502.7,502.7
XS GIS Cut Line= 6
1656227.15362093380063.5643180011656106.75359926380201.573228344
1656050.34196667380251.1144678441655911.69723085380357.937745005
1655846.30431701380417.6459589151655780.63154809380487.110058844
#Sta/Elev= 30
       0 1017.22     6.5 1013.96    32.6  995.83    45.4  985.47    63.9  978.03
    73.8   972.2      88  971.17    93.7  969.09   119.2  950.53   138.5  941.68
   167.3  923.63   195.7  909.48   213.3  898.62   242.2  877.73   267.2  865.13
   283.8  853.32   304.1847.3184   311.4  846.67   316.4  847.32   323.7  850.21
   346.6  850.63   366.4  849.17   397.3  850.74   412.5  850.13   443.3  866.86
   478.7  881.22   521.8   910.3   542.5   918.9   573.5  937.47   617.4  958.25
#Mann= 5, -1 ,  0
       0     0.1       0   304.1   0.045       0   316.4     0.1       0
  388.27    0.06       0  541.84    0.08       0
#XS Ineff= 2 , 0
                          394.03          857.84
Permanent Ineff=
       F       F
Bank Sta=304.1,316.4
XS Rating Curve= 0 ,0
Exp/Cntr(USF)=0,0
Exp/Cntr=0.3,0.1

Type RM Length L Ch R = 1 ,1498    ,497.8,497.8,497.8
XS GIS Cut Line= 6
1655964.42645609379771.7686417551655747.94132476379908.875322923
1655656.01467134379960.8850614281655584.09913276380003.303939834
1655503.36865117380054.0469485821655420.37865968380109.529449165
#Sta/Elev= 30
       0 1008.95    12.4 1001.42      24  992.75    38.2  978.25    53.8  975.44
    73.3  967.74    99.3  949.33     114  942.65   128.2  934.26   147.1   920.6
   163.1  910.74     204  891.52   232.7  876.25   271.8  860.69   283.6  853.62
   297.4  841.43   301.9839.6215   311.2  839.23   316.9 839.625   346.9   842.6
     371   842.3   390.8  845.91   431.4   847.6     455  850.11   473.7   853.3
   506.8  870.94   530.4  877.31   599.6  915.95     617  922.32   640.5  937.13
#Mann= 6, -1 ,  0
       0     0.1       0   301.9   0.045       0   316.9    0.06       0
  381.87     0.1       0  495.36    0.06       0  505.36     0.1       0
Bank Sta=301.9,316.9
XS Rating Curve= 0 ,0
Exp/Cntr(USF)=0,0
Exp/Cntr=0.3,0.1

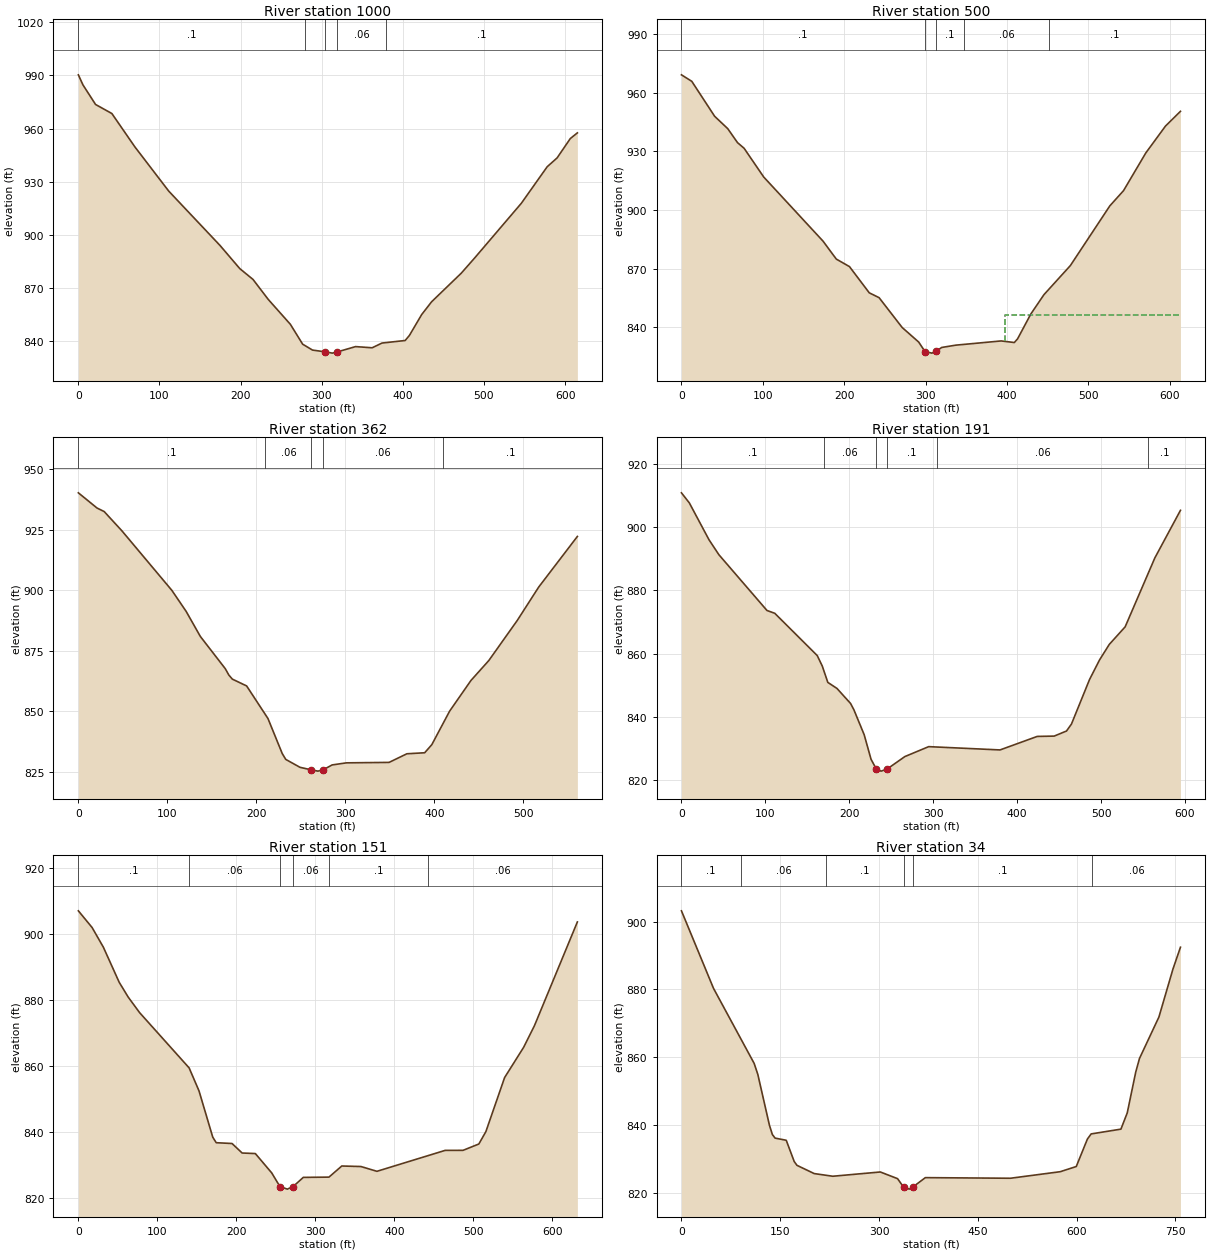
Type RM Length L Ch R = 1 ,1000    ,499.8,499.8,499.8
XS GIS Cut Line= 6
1655813.09605008379495.0772660081655719.09131683379507.636624083
1655631.43433993379520.1753129211655557.41644333379535.028629676
1655459.26572101379554.1768853371655207.56970209379602.315896675
#Sta/Elev= 30
       0  990.36     5.7  984.64    21.2   973.6    41.3  968.47    69.6  949.66
   111.4   924.6   174.6  893.87     199  880.77   215.3  874.64   234.1  863.33
   261.3  849.29   276.5  838.03   288.6  834.71   304.4 833.688   313.2  832.98
   319.3  833.69   341.7  836.67   362.1     836   374.3  838.68   402.8  840.12
   408.1  843.01   423.2  854.79   435.4  862.01     472   878.2   488.3  886.69
   546.1  917.76   577.9  938.38   590.1  943.37   606.4  954.32   615.1  957.53
#Mann= 5, -1 ,  0
       0     0.1       0  278.88    0.06       0   304.4   0.045       0
   319.3    0.06       0  378.88     0.1       0
Bank Sta=304.4,319.3
XS Rating Curve= 0 ,0
Exp/Cntr(USF)=0,0
Exp/Cntr=0.3,0.1

Type RM Length L Ch R = 1 ,500     ,138.4,138.4,138.4
XS GIS Cut Line= 6
1655784.77261592379014.5752742591655690.86630768379022.793105587
1655604.49443318379036.7989830821655431.75134034379064.813690841
1655271.34680551379090.8264340911655177.81615268379100.060011417
#Sta/Elev= 30
       0   969.2    12.7  965.87    40.8  947.96    56.9  941.63    68.9  934.47
      77  931.58   101.1  916.87     174  884.03   190.3  874.84   206.5  870.98
   230.8  857.57   242.9  855.07   271.3  839.78   291.6  832.33   299.3827.4757
   307.8  826.67   312.7827.5125   319.9  829.58   337.3  830.76   392.9  832.91
   409.1   832.1   413.1  833.98   429.3  846.64   445.5   856.6     478  871.52
   526.5  902.09   543.3  909.87   570.7  929.19   594.9  942.96   613.3  950.51
#Mann= 5, -1 ,  0
       0     0.1       0   299.3   0.045       0   312.7     0.1       0
  346.77    0.06       0  451.77     0.1       0
#XS Ineff= 1 ,-1
  397.99613.2507  846.04
Permanent Ineff=
       F
Bank Sta=299.3,312.7
XS Rating Curve= 0 ,0
Exp/Cntr(USF)=0,0
Exp/Cntr=0.3,0.1

Type RM Length L Ch R = 1 ,362     ,170.5,170.5,170.5
XS GIS Cut Line= 2
1655749.13377073378912.0330745261655188.59649336 378930.06644538
#Sta/Elev= 30
       0  940.17      21  933.88      29  932.44      49  924.44   105.1  899.85
   121.1  891.19   137.1  880.81   165.1   867.5   169.1  864.87   173.1  863.17
   189.1  860.37   213.1  846.89   229.1  832.44   233.1     830   249.1  826.73
   261.9825.6843   269.2  825.16     275825.6955   285.2  827.72   301.2  828.58
   349.2  828.77   369.2  832.33   389.2  832.75   397.2  836.09   417.2  849.93
   441.2  862.62   461.3  870.87   493.3  887.46   517.4  901.25   560.8  922.14
#Mann= 5, -1 ,  0
       0     0.1       0     210    0.06       0   261.9   0.045       0
     275    0.06       0     410     0.1       0
Bank Sta=261.9,275
XS Rating Curve= 0 ,0
Exp/Cntr(USF)=0,0
Exp/Cntr=0.3,0.1

Type RM Length L Ch R = 1 ,191     ,40.2,40.2,40.2
XS GIS Cut Line= 4
1655694.99458586378862.7794303821655566.81789418378744.462484212
1655327.99294728 378781.710411711655175.71465545378874.830230455
#Sta/Elev= 30
       0  910.87     9.4  907.68    32.8  896.05    44.6  891.31   101.9  873.68
   111.2  872.79   161.8  859.43   167.8  856.11   174.4  850.95   185.3  849.04
   201.5  844.29   205.5  842.28   217.7  834.43   225.9  826.65   232.3823.5107
   237.9   822.9   244.8823.5131   266.2   827.5   294.6  830.64   379.6   829.6
   423.9  833.87   444.1  833.97   458.8  835.58   464.7  837.77   486.3  851.88
   498.2  858.06   509.8  862.96   528.7  868.51   564.1  890.31   594.6  905.34
#Mann= 6, -1 ,  0
       0     0.1       0     170    0.06       0   232.3   0.045       0
   244.8     0.1       0  304.44    0.06       0  556.15     0.1       0
Bank Sta=232.3,244.8
XS Rating Curve= 0 ,0
Exp/Cntr(USF)=0,0
Exp/Cntr=0.3,0.1

Type RM Length L Ch R = 1 ,151     ,116.8,116.8,116.8
XS GIS Cut Line= 4
1655718.00065873378831.0091392811655552.57603955378706.119029434
1655349.90349287378738.9848478151655155.99516442378840.868884795
#Sta/Elev= 30
       0  907.07    17.4     902    31.7  896.02    51.7   885.4    63.1  880.91
    77.5  876.21   140.2  859.45   152.7  852.49   170.1  838.45   174.5  836.77
   194.5  836.53   207.3  833.65     224  833.48   244.7  827.63   255.1823.4883
   264.5   822.7   271.8823.4791   284.7  826.26   317.2  826.34   333.4  829.71
   357.7  829.55   377.9   828.1   464.3  834.45   486.9  834.46   506.9  836.38
   515.8  840.14   539.5  856.52   563.7  865.74   577.3  872.27   631.6   903.7
#Mann= 6, -1 ,  0
       0     0.1       0     140    0.06       0   255.1   0.045       0
   271.8    0.06       0  317.27     0.1       0  442.59    0.06       0
Bank Sta=255.1,271.8
XS Rating Curve= 0 ,0
Exp/Cntr(USF)=0,0
Exp/Cntr=0.3,0.1

Type RM Length L Ch R = 1 ,34      ,,,
XS GIS Cut Line= 4
1655733.19196755378812.3684569491655526.16261324378595.479357131
1655343.08100461378614.7396413791655149.90443859378808.611973739
#Sta/Elev= 30
       0  903.15    48.7  880.26   110.4  858.12   115.9  854.92   133.6  839.86
     138  837.16   142.1  836.09   159.1  835.44   171.2  829.17   175.4  828.05
   201.5  825.62   229.8  824.83   301.9  826.09   328.1  824.12337.2039821.6265
   346.1  821.03350.9038821.5893   370.3  824.42   499.5  824.24     575  826.17
   599.4   827.7   616.3   835.8     622  837.32   667.2  838.73   676.8  843.52
   689.7  855.57   695.4  859.59   724.9  871.82   746.2  885.97   757.6  892.41
#Mann= 6, -1 ,  0
       0     0.1       0      90    0.06       0     220     0.1       0
337.2039   0.045       0350.9038     0.1       0  623.93    0.06       0
Bank Sta=337.2039,350.9038
XS Rating Curve= 0 ,0
Exp/Cntr(USF)=0,0
Exp/Cntr=0.3,0.1
LCMann Table=0

Chan Stop Cuts=-1
Use User Specified Reach Order=0
Composite Channel Slope=5